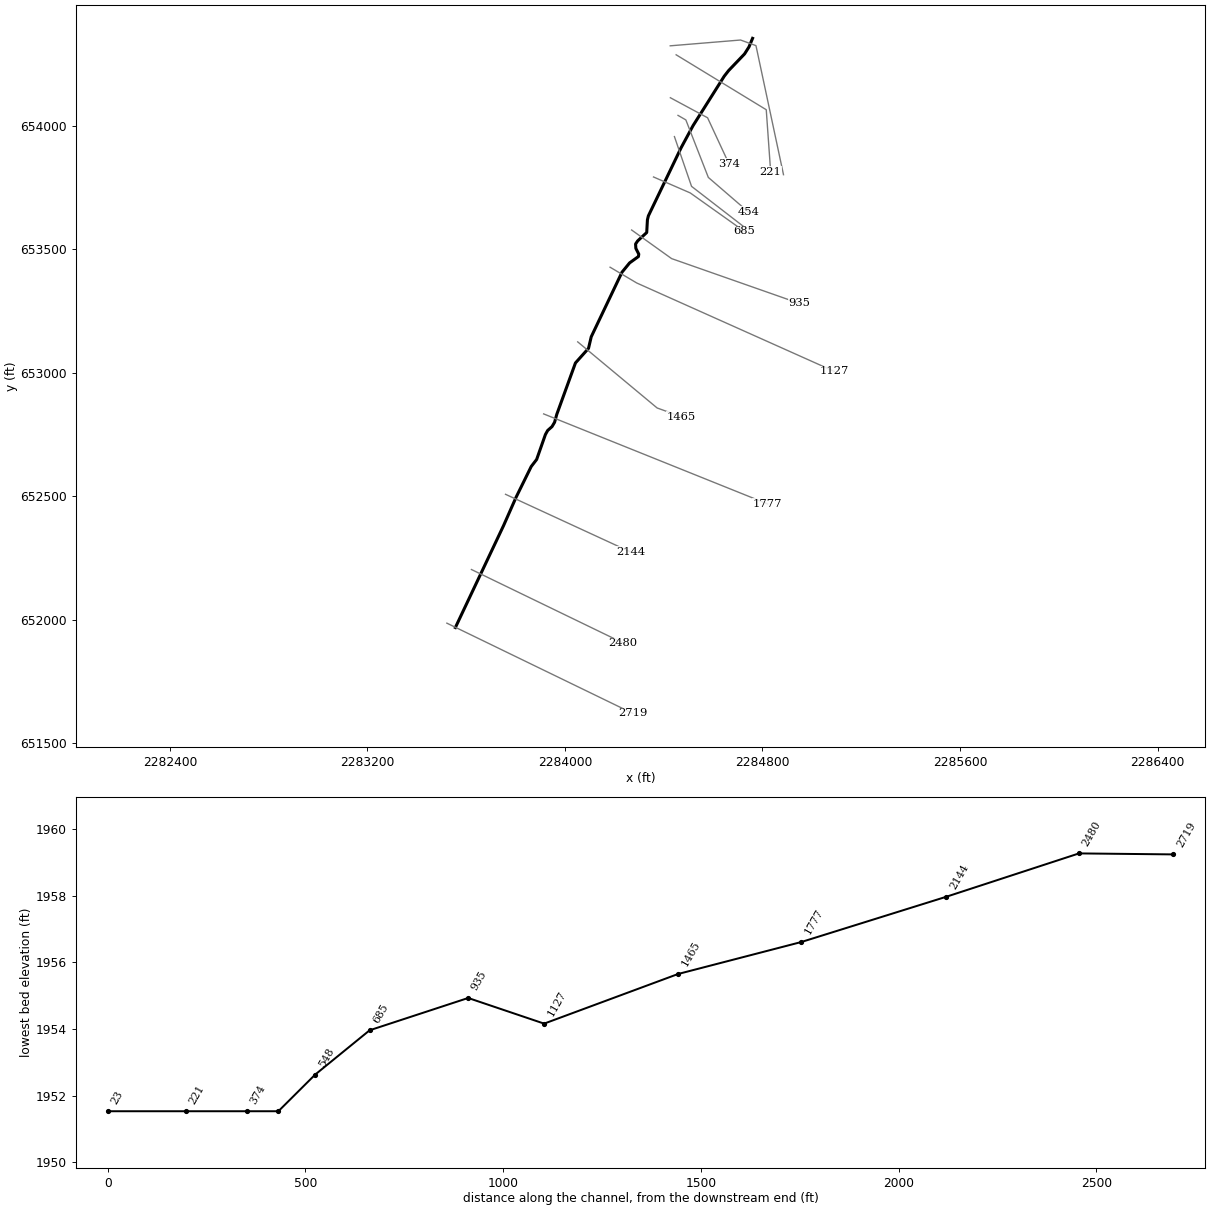
--- SEARN.prj (project) ---

Proj Title=SEARN
Current Plan=p01
Default Exp/Contr=0,0
English Units
Geom File=g01
Flow File=f01
Plan File=p01
BEGIN DESCRIPTION:
----------MODEL BY WOOD PLC 2022----------
AFH study
Randolph County, WV
HEC-RAS Version: RAS 6.2
Vertical Datum: NAVD88
Projection: NAD 1983 StatePlane West Virginia S FIPS 4702 (US Feet)
Terrain: 1-meter LIDAR (FEMA Region III 3DEP collected 2016-2018)
Land Use: 2019 NLCD
Hydrologic Method:
WV SIR2010-5033 regression equations
Additional Model Notes:
FP between XS 2480 and 2719 on LOB is unbounded; floodplain to be trimmed on high ground by mapping
END DESCRIPTION:
DSS Export Rating Curves= 0
DSS Export Rating Curve Sorted= 0
DSS Export Volume Flow Curves= 0
DXF OffsetX= 0
DXF OffsetY= 0
DXF ScaleX= 0
DXF ScaleY= 0

--- SEARN.p01 (plan) ---

Plan Title=Floodplain
Program Version=6.20
Short Identifier=Floodplain
Geom File=g01
Flow File=f01
Subcritical Flow
K Sum by GR= 0
Std Step Tol= 0.01
Critical Tol= 0.01
Num of Std Step Trials= 20
Max Error Tol= 0.3
Flow Tol Ratio= 0.001
Split Flow NTrial= 30
Split Flow Tol= 0.02
Split Flow Ratio= 0.02
Log Output Level= 0
Friction Slope Method= 1
Unsteady Friction Slope Method= 2
Unsteady Bridges Friction Slope Method= 1
Parabolic Critical Depth
Global Vel Dist= 0 , 0 , 0
Global Log Level= 0
CheckData=True
Encroach Param=-1 ,0,0, 0
Mapping Interval=1HOUR
Computation Time Step Use Courant=        0
Computation Time Step Use Time Series=    0
Computation Time Step Count To Double=0
Computation Time Step Max Doubling=0
Computation Time Step Max Halving=0
Computation Time Step Residence Courant=0
Run HTab= 0
Run UNet= 0
Run Sediment= 0
Run PostProcess= 0
Run WQNet= 0
Run RASMapper=-1
UNET Theta= 0
UNET Theta Warmup= 0
UNET ZTol= 0
UNET ZSATol= 0
UNET MxIter= 0
UNET Max Iter WO Improvement= 0
UNET MaxInSteps= 0
UNET DtIC= 0
UNET DtMin= 0
UNET MaxCRTS= 0
UNET WFStab= 0
UNET SFStab= 0
UNET WFX= 1
UNET SFX= 1
UNET Gravity=32.174
UNET 1D Methodology=Finite Difference
UNET DSS MLevel= 1
UNET Pardiso=0
UNET DZMax Abort= 0
UNET Use Existing IB Tables= 0
UNET Froude Reduction=False
UNET Froude Limit= 0
UNET Froude Power= 0
UNET D1 Cores= 0
UNET WindReference=Eulerian
UNET WindDragFormulation=Hsu (1988)
UNET D2 Coriolis=0
UNET D2 Cores= 0
UNET D2 Theta= 1
UNET D2 Theta Warmup= 1
UNET D2 Z Tol= 0.01
UNET D2 Volume Tol= 0.01
UNET D2 Max Iterations= 20
UNET D2 Equation= 0
UNET D2 RampUpFraction=0.1
UNET D2 TimeSlices= 1
UNET D2 Turbulence Formulation=Non-Conservative (original)
UNET D2 Eddy Viscosity=0.3
UNET D2 Transverse Eddy Viscosity=0.1
UNET D2 Smagorinsky Mixing=0
UNET D2 BCVolumeCheck=0
UNET D2 Cores=0
UNET D2 SolverType=PARDISO (Direct)
UNET D2 Minimum Iterations= 2147483647
UNET D2 Maximum Iterations= 2147483647
UNET D2 Restart Number= 10
UNET D2 Relaxation Coeff=1.3
UNET D2 SOR Precondition Iterations= 10
UNET D2 ILUT Maximum Fill= 8
UNET D2 ILUT Tolerance=1E-08
UNET D1D2 MaxIter= 0
UNET D1D2 ZTol=0.01
UNET D1D2 QTol=0.1
UNET D1D2 MinQTol=1
Write IC File= 0
Write IC File at Fixed DateTime=0
Write IC File at Sim End=0
Echo Input=False
Echo Parameters=False
Echo Output=False
Write Detailed= 0
HDF Write Warmup=0
HDF Write Time Slices=0
HDF Flush=0
HDF Compression= 1
HDF Chunk Size= 1
HDF Spatial Parts= 1
HDF Use Max Rows=0
HDF Fixed Rows= 1
Calibration Method= 0
Calibration Iterations= 20
Calibration Max Change=0.05
Calibration Tolerance=0.2
Calibration Maximum=1.5
Calibration Minimum=0.5
Calibration Optimization Method= 1
WQ AD Non Conservative
WQ ULTIMATE=-1
WQ Max Comp Step=1HOUR
WQ Output Interval=15MIN
WQ Output Selected Increments= 0
WQ Output face flow=0
WQ Output face velocity=0
WQ Output face area=0
WQ Output face dispersion=0
WQ Output cell volume=0
WQ Output cell surface area=0
WQ Output cell continuity=0
WQ Output cumulative cell continuity=0
WQ Output face conc=0
WQ Output face dconc_dx=0
WQ Output face courant=0
WQ Output face peclet=0
WQ Output face adv mass=0
WQ Output face disp mass=0
WQ Output cell mass=0
WQ Output cell source sink temp=0
WQ Output nsm pathways=0
WQ Output nsm derived pathways=0
WQ Create Restart=0
WQ Fixed Restart=0
WQ System Summary=0
WQ Write To DSS=0
Sorting and Armoring Iterations= 10
XS Update Threshold= 0.02
Bed Roughness Predictor= 0
Hydraulics Update Threshold= 0.02
Energy Slope Method= 1
Volume Change Method= 1
Sediment Retention Method= 0
Sediment TS Multiplier= 1
Warm Up Method= 0
XS Weighting Method= 0
Number of US Weighted Cross Sections= 1
Number of DS Weighted Cross Sections= 1
Upstream XS Weight=0
Main XS Weight=1
Downstream XS Weight=0
Number of DS XS's Weighted with US Boundary= 1
Upstream Boundary Weight= 1
Weight of XSs Associated with US Boundary= 0
Number of US XS's Weighted with DS Boundary= 1
Downstream Boundary Weight= 0.5
Weight of XSs Associated with DS Boundary= 0.5
Percentile Method= 0
Sediment Output Level= 3
Mass or Volume Output= 0
Output Increment Type= 1
Profile and TS Output Increment= 1
Transport Output Increment 1
XS Output Flag= 0
XS Output Increment= 10
Read HDF5 Sediment Hotstart= 0
Sediment Hotstart Type= 0
Write Gradation File= 0
Read Gradation Hotstart= 0
Write HDF5 File= 1
Write Binary Output= 1
Write DSS Sediment File= 0
DSS Sediment Output Type= 1
SV Curve= 0
Specific Gage Flag= 0
Subcell Erosion Methods= 0
Subcell Deposition Methods= 0
Advection Scheme= 1
Matrix Solver= 0
Implicit Weighting Factor= 1
Maximum Outer Loop Convergence Iterations= 5
Convergence Maximum Absolute= 0.001
Convergence RMSE= 0.0001
Grain Fractions Max Abs Error= 0.001
Max Subgrid Regions= 1
Max Subgrid Length Scale= 3.402823E+38
Initial Layer Thickness= 3.402823E+38
Min Layer Thickness= 3.402823E+38
Max Layer Thickness= 3.402823E+38
Number of Layers= 5

--- SEARN.f01 (steady flow) ---

Flow Title=Flow
Program Version=6.20
Number of Profiles= 1
Profile Names=P100yr
River Rch & RM=SEARN,Main            ,2719
     540
River Rch & RM=SEARN,Main            ,2144
     691
Boundary for River Rch & Prof#=SEARN,Main            , 1
Up Type= 0
Dn Type= 3
Dn Slope=0.01123
DSS Import GetInterval= 0
DSS Import GetPeak= 0
DSS Import FillOption= 0

--- SEARN.g01 (geometry) ---

Geom Title=Geometry
Program Version=6.20

River Reach=SEARN           ,Main
Reach XY= 30
      2283556.25      651968.779     2283751.331      652381.402
     2283802.198       652496.53     2283863.461      652620.902
     2283885.383      652649.439      2283920.84      652750.292
     2283930.053      652766.851     2283947.585      652782.427
     2283957.991      652799.996     2283966.856      652831.907
     2284042.564      653040.343     2284095.445      653099.446
     2284106.439       653146.16     2284230.991      653407.757
     2284261.874      653445.504     2284297.519      653471.261
     2284299.086      653480.965     2284287.168      653504.303
     2284286.035      653522.071      2284294.46      653534.511
     2284331.186      653568.562     2284334.002      653619.642
     2284337.869      653635.845      2284470.62       653912.15
     2284519.005      654001.664     2284645.006      654201.468
     2284662.997      654224.573      2284727.35      654291.735
     2284745.243       654320.02     2284759.911      654354.997

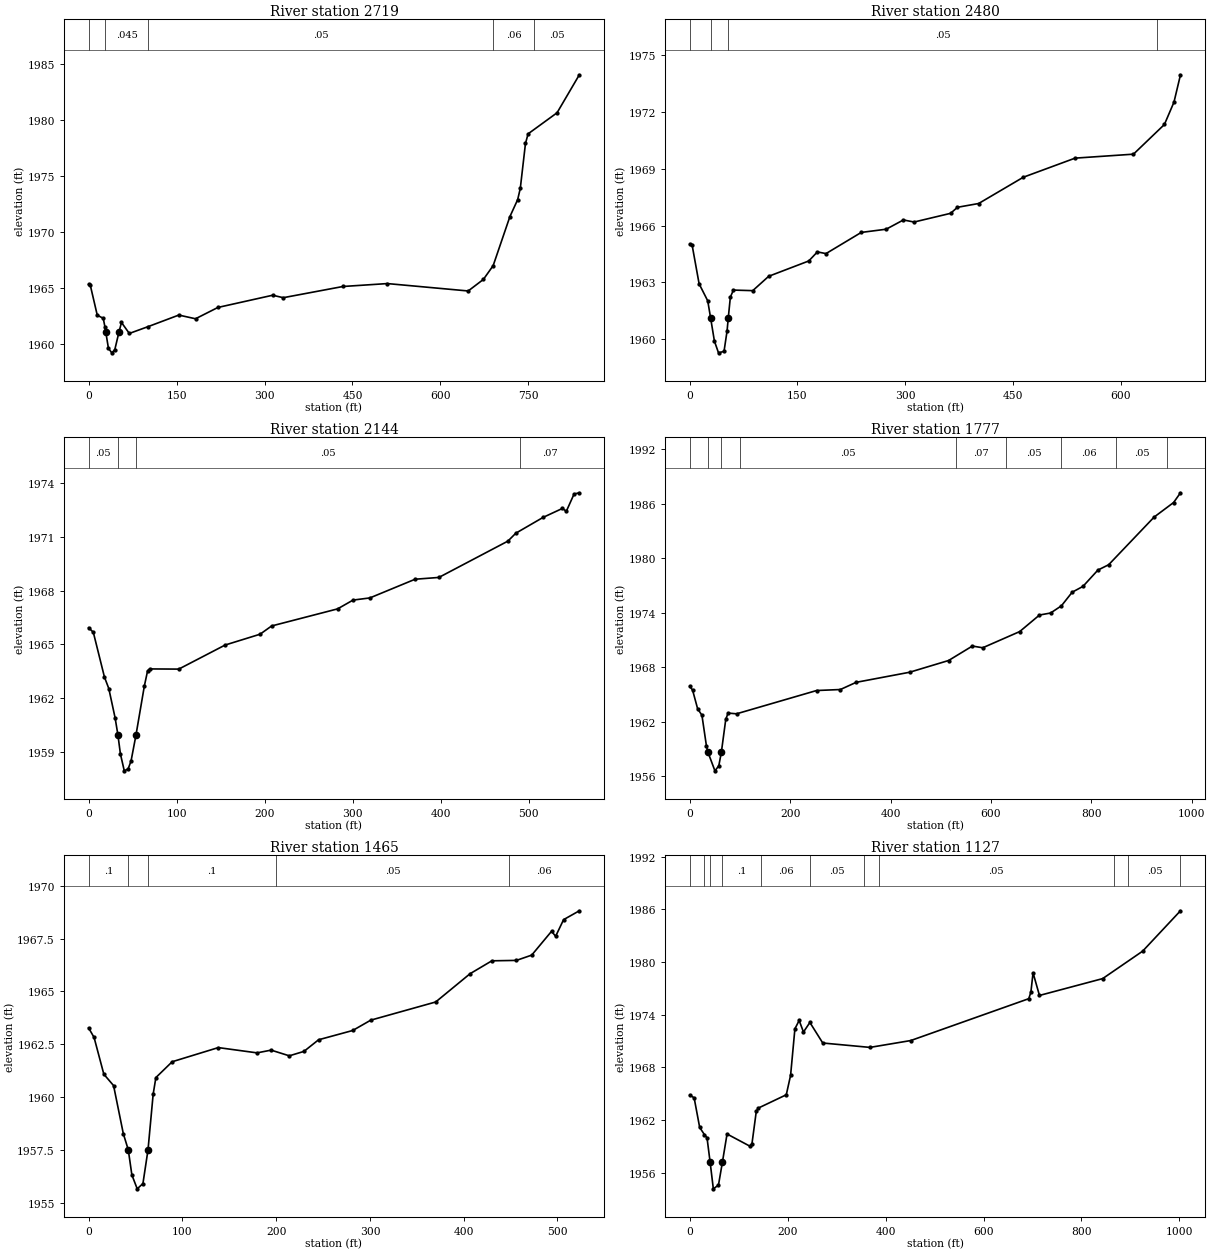
Type RM Length L Ch R = 1 ,2719    ,239,238.9,239
XS GIS Cut Line= 2
2283521.77602959651986.4413433472284274.75152137 651621.03424815
#Sta/Elev= 30
       0 1965.35     2.7  1965.3    14.7  1962.6    24.9 1962.32   27.691961.586
    29.3 1961.07    33.8 1959.64    39.5 1959.24    44.6 1959.52    51.6 1961.06
      56 1961.95    69.4 1960.97  101.741961.585   153.8 1962.61   182.3 1962.28
   220.5 1963.29   313.9 1964.38     332 1964.16   433.8 1965.16   509.5 1965.42
   647.4 1964.76   673.3 1965.79     690 1967.02   718.5 1971.39   731.8 1972.91
   736.3 1973.92   745.1 1977.92   749.6 1978.78     799 1980.66     837 1984.05
#Mann= 5 ,-1,0
       0     .05       0   27.69    .045       0  101.74     .05       0
     690     .06       0     760     .05       0
Bank Sta=29.3,51.6
XS Rating Curve= 0 ,0
Exp/Cntr(USF)=0,0
Exp/Cntr=0.3,0.1

Type RM Length L Ch R = 1 ,2480    ,335.1,335.3,335.5
XS GIS Cut Line= 2
2283621.28530583652203.6822898652284236.37535352651905.761123909
#Sta/Elev= 30
       0 1965.03     3.2 1964.98      13 1962.92      25 1962.02   29.021961.112
    34.3 1959.89      40 1959.27    47.7 1959.35    51.9 1960.42   53.59 1961.11
    56.5 1962.22    60.8 1962.59    87.7 1962.56   109.9 1963.32   165.7 1964.13
   177.7 1964.61   189.7 1964.52   238.8 1965.64   273.5 1965.81   297.5  1966.3
   312.4 1966.19   363.2 1966.65   372.8 1966.97   402.3 1967.17   464.5 1968.56
   536.6 1969.57   617.9 1969.78     661 1971.35   674.3 1972.53   683.4 1973.98
#Mann= 4 ,-1,0
       0     .05       0   29.02    .045       0   53.59     .05       0
     650     .06       0
Bank Sta=29.02,53.59
XS Rating Curve= 0 ,0
Exp/Cntr(USF)=0,0
Exp/Cntr=0.3,0.1

Type RM Length L Ch R = 1 ,2144    ,365.3,367,367
XS GIS Cut Line= 2
 2283759.3667451652508.2983134842284265.66535579652274.815152524
#Sta/Elev= 30
       0 1965.93     5.3 1965.68      18 1963.18    22.9 1962.55    30.1 1960.91
   33.291959.959    36.1 1958.91    40.5 1957.97    44.9 1958.08    48.2 1958.52
   53.781959.961    63.3 1962.69      67 1963.54    69.3 1963.64   102.4 1963.63
   155.1 1964.97   194.7 1965.57   207.9 1966.03   282.8 1966.98   300.4 1967.47
   319.5 1967.59   370.9 1968.63   397.9 1968.73   476.3 1970.75   485.3 1971.19
   516.3 1972.07   538.3 1972.57   542.7 1972.41   551.5 1973.37   557.5 1973.44
#Mann= 4 ,-1,0
       0     .05       0   33.29    .045       0   53.78     .05       0
     490     .07       0
Bank Sta=33.29,53.78
XS Rating Curve= 0 ,0
Exp/Cntr(USF)=0,0
Exp/Cntr=0.3,0.1

Type RM Length L Ch R = 1 ,1777    ,314.5,311.7,307.8
XS GIS Cut Line= 2
2283913.69329809652833.9466924932284820.91623084652469.178878031
#Sta/Elev= 30
       0 1965.91     5.6 1965.48    15.6 1963.44    24.2 1962.72    33.2 1959.34
   36.221958.656    50.1 1956.61    57.8 1957.16   62.921958.656    71.7 1962.27
    76.3 1962.96    93.2 1962.88   252.7 1965.44   300.1 1965.55   331.5 1966.34
   438.1 1967.45   515.7 1968.74   563.1 1970.33   583.7 1970.14   657.4 1971.92
   696.8 1973.74   718.9 1973.96   740.5 1974.75     762 1976.25   783.5 1976.89
   813.2 1978.68   834.7 1979.27   925.3 1984.51   964.1 1986.11   977.8 1987.18
#Mann= 9 ,-1,0
       0      .1       0   36.22    .045       0   62.92      .1       0
     100     .05       0     530     .07       0     630     .05       0
     740     .06       0     850     .05       0     950     .06       0
Bank Sta=36.22,62.92
XS Rating Curve= 0 ,0
Exp/Cntr(USF)=0,0
Exp/Cntr=0.3,0.1

Type RM Length L Ch R = 1 ,1465    ,337.2,338.8,340
XS GIS Cut Line= 3
 2284051.7041153653125.6607964772284373.42921961652857.866489999
2284471.99240186652822.532519005
#Sta/Elev= 30
       0 1963.27     5.8 1962.82    16.2 1961.08    26.6 1960.54      37 1958.26
   42.271957.499    46.1 1956.31    51.8 1955.65    57.9  1955.9   63.321957.499
    68.8 1960.13    71.7 1960.92    89.1 1961.67   138.3 1962.34   179.6 1962.09
   194.6 1962.22     214 1961.95   229.6 1962.16   245.2 1962.71   281.6 1963.15
   300.9 1963.64   370.1  1964.5   406.8 1965.84     430 1966.45   456.2 1966.47
   472.5 1966.72   493.7 1967.85     498 1967.61   506.5  1968.4   523.3 1968.82
#Mann= 5 ,-1,0
       0      .1       0   42.27    .045       0   63.32      .1       0
     200     .05       0  448.59     .06       0
Bank Sta=42.27,63.32
XS Rating Curve= 0 ,0
Exp/Cntr(USF)=0,0
Exp/Cntr=0.3,0.1

Type RM Length L Ch R = 1 ,1127    ,190.6,192.1,188.4
XS GIS Cut Line= 3
2284182.77104787653428.0340838622284290.94976344653364.061813864
2285091.05367649 653006.00385541
#Sta/Elev= 30
       0 1964.85     8.9 1964.53    20.2 1961.16      30 1960.33    35.2 1959.98
   41.571957.188    48.1 1954.16    58.6 1954.59   66.591957.185    76.1 1960.41
   122.5 1959.03     127  1959.3   135.8 1962.98   140.2 1963.37   197.1 1964.88
   205.9  1967.1   214.7  1972.4   223.4 1973.35   232.2 1972.03   245.3 1973.12
   271.6 1970.78     368 1970.28   451.3 1971.06   692.3 1975.83   696.7 1976.57
   701.1 1978.78   714.2  1976.2   843.3 1978.12     925 1981.25  1002.2 1985.85
#Mann= 11 ,-1,0
       0     .05       0      30      .1       0   41.57    .045       0
   66.59      .1       0  145.68     .06       0  245.68     .05       0
  355.68     .06       0  385.68     .05       0  865.68     .06       0
  895.68     .05       0 1002.25     .06       0
Bank Sta=41.57,66.59
XS Rating Curve= 0 ,0
Exp/Cntr(USF)=0,0
Exp/Cntr=0.3,0.1

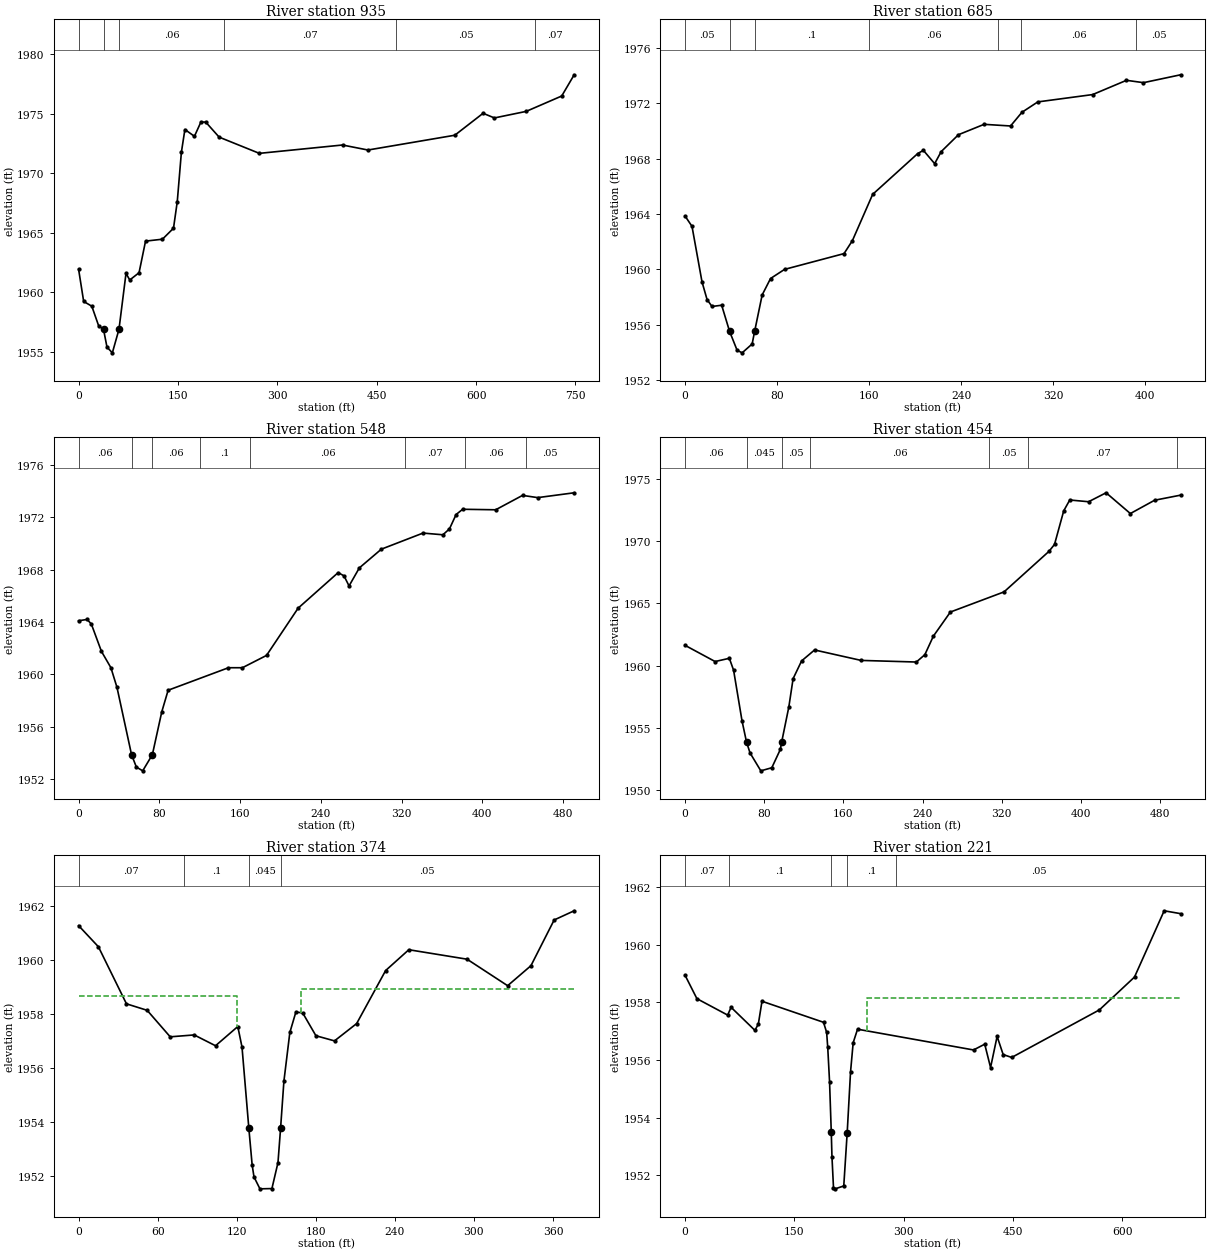
Type RM Length L Ch R = 1 ,935     ,245.7,249.3,250.6
XS GIS Cut Line= 3
 2284270.0215148653578.7786518682284432.02870165653462.865560023
2284949.90941609653281.200597366
#Sta/Elev= 30
       0 1961.92     7.6 1959.24    19.9 1958.84    30.2  1957.2   37.561956.901
    42.8 1955.41    50.9 1954.93    60.91956.901    71.5 1961.59    77.2 1961.04
    91.2 1961.65     101  1964.3   126.5 1964.46   143.2 1965.38   148.9 1967.62
   155.1 1971.75   160.4 1973.66   174.8 1973.09   184.6 1974.29   191.9 1974.28
   212.1 1973.02   272.8 1971.66   398.3 1972.36   436.7 1971.94   567.8 1973.18
   610.5 1975.02   627.6 1974.63   675.6 1975.18   729.2 1976.47     748 1978.25
#Mann= 6 ,-1,0
       0      .1       0   37.56    .045       0    60.9     .06       0
   219.2     .07       0   479.2     .05       0   689.2     .07       0
Bank Sta=37.56,60.9
XS Rating Curve= 0 ,0
Exp/Cntr(USF)=0,0
Exp/Cntr=0.3,0.1

Type RM Length L Ch R = 1 ,685     ,145.4,137.7,129.9
XS GIS Cut Line= 3
2284358.69657939653793.4966250132284507.55339208653728.829321141
2284726.56812878653573.261750508
#Sta/Elev= 30
       0 1963.84       6  1963.1    14.7 1959.09    19.1 1957.81    23.4 1957.31
    31.8  1957.4   38.651955.518    45.2 1954.15    49.6 1953.96    58.3  1954.6
   60.471955.518      67 1958.14    74.3 1959.33    86.5 1959.99   138.2 1961.13
   145.5 1962.07   163.1 1965.41   202.3 1968.36   207.2 1968.59     217 1967.63
   222.7  1968.5   237.7 1969.72     260 1970.47     283 1970.35   292.9 1971.34
   306.7 1972.09   354.4 1972.62   383.8 1973.65   398.6 1973.48   430.9 1974.05
#Mann= 7 ,-1,0
       0     .05       0   38.65    .045       0   60.47      .1       0
     160     .06       0   272.3     .07       0   292.3     .06       0
   392.3     .05       0
Bank Sta=38.65,60.47
XS Rating Curve= 0 ,0
Exp/Cntr(USF)=0,0
Exp/Cntr=0.3,0.1

Type RM Length L Ch R = 1 ,548     ,101.1,93.1,91.6
XS GIS Cut Line= 3
2284443.38414555653957.0851061662284512.73027854653755.522062217
2284732.74362673653585.621442726
#Sta/Elev= 30
       0  1964.1     8.4  1964.2    12.6 1963.85    22.6 1961.76      32 1960.51
      38 1959.01   52.431953.868    57.2 1952.92    63.5 1952.63   73.081953.867
    82.4 1957.14    88.7 1958.79   148.5 1960.51   162.3 1960.51   186.2 1961.45
   217.5 1965.06   257.2 1967.78     263 1967.53     268 1966.76   278.2 1968.14
     300 1969.57   341.3  1970.8     361 1970.67   367.5 1971.12   374.1 1972.22
   380.6 1972.62   413.3 1972.58   439.9 1973.68     455 1973.51   491.1 1973.88
#Mann= 8 ,-1,0
       0     .06       0   52.43    .045       0   73.08     .06       0
     120      .1       0     170     .06       0  323.16     .07       0
  383.16     .06       0  443.16     .05       0
Bank Sta=52.43,73.08
XS Rating Curve= 0 ,0
Exp/Cntr(USF)=0,0
Exp/Cntr=0.3,0.1

Type RM Length L Ch R = 1 ,454     ,66.9,80.3,89.3
XS GIS Cut Line= 4
2284457.89431405654042.9465590772284489.65432314654024.616438065
2284580.72270329653791.6789066262284742.60991993653652.038720068
#Sta/Elev= 30
       0 1961.62    30.3 1960.32    44.7 1960.58      49 1959.62    57.5 1955.55
   62.031953.853    65.6 1952.97    76.5 1951.53    87.6 1951.78    96.2 1953.25
   97.591953.856   104.8 1956.67   109.1 1958.94   117.7 1960.37   130.8 1961.25
   177.8 1960.41   233.6 1960.28   242.2 1960.87   250.8 1962.36     268  1964.3
   322.2 1965.92   367.6 1969.18   373.2 1969.74   382.5 1972.44   388.6 1973.31
   407.6 1973.17   425.3 1973.89   449.8 1972.22   474.3 1973.29   500.6  1973.7
#Mann= 7 ,-1,0
       0     .06       0   62.03    .045       0   97.59     .05       0
  126.67     .06       0  306.78     .05       0  346.78     .07       0
  496.78     .05       0
Bank Sta=62.03,97.59
XS Rating Curve= 0 ,0
Exp/Cntr(USF)=0,0
Exp/Cntr=0.3,0.1

Type RM Length L Ch R = 1 ,374     ,153.7,153.3,152.4
XS GIS Cut Line= 3
 2284426.9677449  654114.39066032284577.64734712654033.323271974
2284664.00173903653847.396979184
#Sta/Elev= 30
       0 1961.26      15 1960.48    36.3 1958.37      52 1958.13    69.5 1957.15
    87.7 1957.22   103.9 1956.82   120.8 1957.53     124 1956.77  129.191953.767
   131.7 1952.41   133.1 1951.97   137.6 1951.53   146.7 1951.54   151.3  1952.5
  153.271953.767   155.8 1955.51   160.3 1957.31   164.9 1958.07   170.1 1958.03
   180.1 1957.19   194.2    1957     211 1957.64     233  1959.6   250.6 1960.37
   294.8 1960.02   325.6 1959.04   343.3 1959.78   360.9 1961.47   376.1 1961.81
#Mann= 4 ,-1,0
       0     .07       0      80      .1       0  129.19    .045       0
  153.27     .05       0
#XS Ineff= 2 , 0
          120.33 1958.67  169.11         1958.91
Permanent Ineff=
       F       F
Bank Sta=129.19,153.27
XS Rating Curve= 0 ,0
Exp/Cntr(USF)=0,0
Exp/Cntr=0.3,0.1

Type RM Length L Ch R = 1 ,221     ,194.6,197.9,199.9
XS GIS Cut Line= 3
 2284450.3356424654288.3388764612284815.28566237654065.853785764
2284833.15252616653814.046142728
#Sta/Elev= 30
       0 1958.94    16.2 1958.13    58.4 1957.56    63.1 1957.83    95.8 1957.03
   100.5 1957.25   105.5 1958.04   189.9 1957.31   194.2 1956.96   195.7 1956.44
   198.2 1955.25  200.571953.487   201.5 1952.65   203.6 1951.57   205.9 1951.53
   217.7 1951.63  222.421953.485     227 1955.59   230.6  1956.6   236.6 1957.07
   395.7 1956.35   411.1 1956.55   419.1 1955.74   428.1 1956.82   436.4 1956.19
   448.1 1956.09   568.4 1957.74   616.6 1958.88   657.3 1961.18   679.9 1961.08
#Mann= 5 ,-1,0
       0     .07       0      60      .1       0  200.57    .045       0
  222.42      .1       0     290     .05       0
#XS Ineff= 2 , 0
                          249.27         1958.15
Permanent Ineff=
       F       F
Bank Sta=200.57,222.42
XS Rating Curve= 0 ,0
Exp/Cntr(USF)=0,0
Exp/Cntr=0.3,0.1

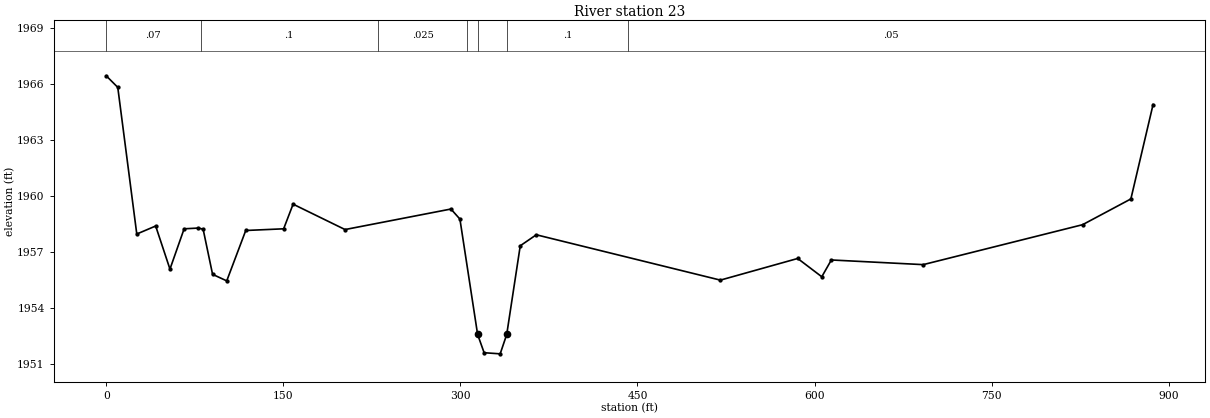
Type RM Length L Ch R = 1 ,23      ,,,
XS GIS Cut Line= 4
2284426.38509234654324.6869940172284711.25457582654348.206371373
2284773.65302991654325.4610268132284885.15112814653802.767018255
#Sta/Elev= 30
       0 1966.43     9.8 1965.81    25.9 1957.95    41.9 1958.38      54 1956.07
      66 1958.23    78.1 1958.27    82.1 1958.21    90.1 1955.79   102.1 1955.44
   118.2 1958.14   150.3 1958.23   158.3 1959.55   202.3 1958.19     292 1959.29
   299.6 1958.75  314.591952.568   320.1 1951.59   333.7 1951.53  339.241952.567
   350.7 1957.32   364.3 1957.91   520.2 1955.48   585.7 1956.64   606.1 1955.66
   614.2 1956.56     692 1956.31     827 1958.45   867.9 1959.83   886.7 1964.89
#Mann= 7 ,-1,0
       0     .07       0      80      .1       0     230    .025       0
  305.84      .1       0  314.59    .045       0  339.24      .1       0
  442.25     .05       0
Bank Sta=314.59,339.24
XS Rating Curve= 0 ,0
Exp/Cntr(USF)=0,0
Exp/Cntr=0.3,0.1
LCMann Table=0

Chan Stop Cuts=-1
Use User Specified Reach Order=0
Composite Channel Slope=5